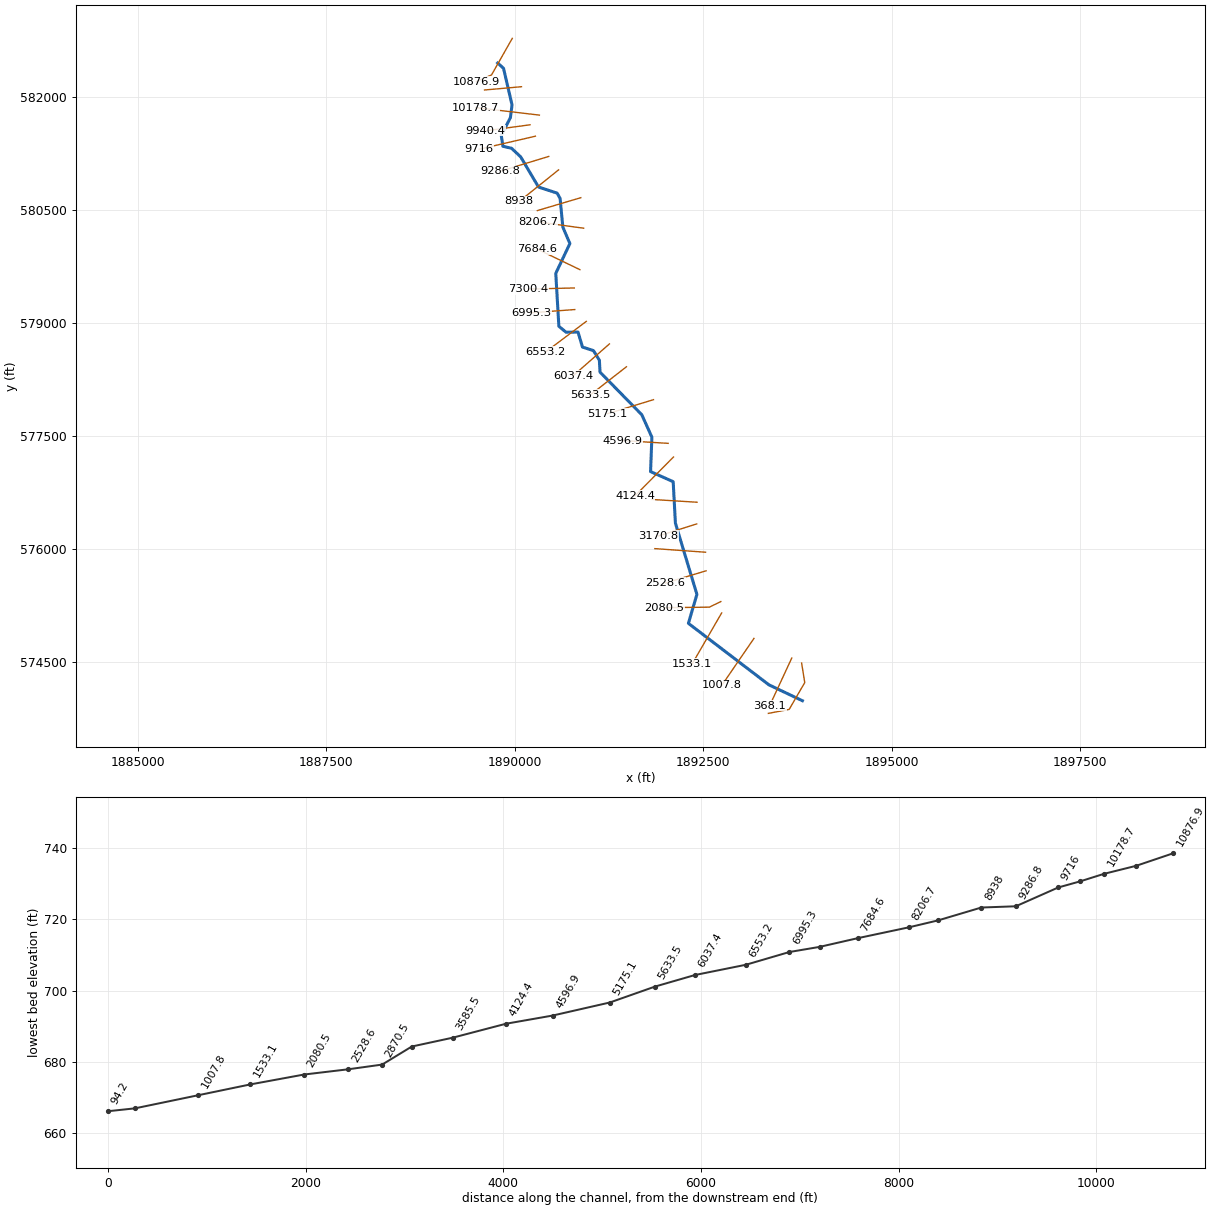
--- LLftHndRun.prj (project) ---

Proj Title=LLftHndRun
Current Plan=p01
Default Exp/Contr=0,0
English Units
Geom File=g01
Flow File=f01
Plan File=p01
BEGIN DESCRIPTION:
AMEC Environment & Infrastructure, 2013
Projection: NAD 1983 State Plane West Virginia South FIPS 4702 (US Feet)
Vertical Datum: NAVD 1988
END DESCRIPTION:
DSS Export Rating Curves= 0
DSS Export Rating Curve Sorted= 0
DSS Export Volume Flow Curves= 0
DXF OffsetX= 0
DXF OffsetY= 0
DXF ScaleX= 0
DXF ScaleY= 0

--- LLftHndRun.p01 (plan) ---

Plan Title=Floodplain
Program Version=4.00
Geom File=g01
Flow File=f01
K Sum by GR=0
Std Step Tol=0.01
Critical Tol=0.01
Num of Std Step Trials=20
Max Error Tol=0.3
Flow Tol Ratio=0.001
Split Flow NTrial=30
Split Flow Tol=0.02
Split Flow Ratio=0.02
Log Output Level=0
Friction Slope Method=1
Unsteady Friction Slope Method=2
Unsteady Bridges Friction Slope Method=1
Global Log Level=0
CheckData=False
Run HTab=0
Run UNet=0
Run PostProcess=0
UNET Theta=0
UNET Theta Warmup=0
UNET ZTol=0
UNET ZSATol=0
UNET MxIter=0
UNET MaxInSteps=0
UNET DtIC=0
UNET DtMin=0
UNET MaxCRTS=0
UNET WFStab=0
UNET SFStab=0
UNET WFX=0
UNET SFX=0
UNET DSS MLevel=0
UNET DZMax Abort=0
UNET Convert EG Bridges=0
UNET Use Existing IB Tables=0
UNET Froude Limit=0
UNET Froude Power=0
Write IC File=0
Echo Input=False
Echo Output=False
Write Detailed=0

--- LLftHndRun.f01 (steady flow) ---

Flow Title=NFF Regression Equation
Program Version=4.10
Number of Profiles= 1
Profile Names=P100yr
River Rch & RM=LLftHndRun,Main            ,10876.9
944.5994
River Rch & RM=LLftHndRun,Main            ,9716
955.5891
River Rch & RM=LLftHndRun,Main            ,7300.4
1060.451
River Rch & RM=LLftHndRun,Main            ,6037.4
1173.116
River Rch & RM=LLftHndRun,Main            ,4124.4
1301.266
River Rch & RM=LLftHndRun,Main            ,368.1
1437.134
Boundary for River Rch & Prof#=LLftHndRun,Main            , 1
Up Type= 0
Dn Type= 3
Dn Slope=0.004991
DSS Import GetInterval= 0
DSS Import GetPeak= 0
DSS Import FillOption= 0

--- LLftHndRun.g01 (geometry) ---

Geom Title=USGS 3m DEM
Program Version=4.10

River Reach=LLftHndRun      ,Main
Reach XY= 30
     1889774.129      582445.516     1889852.186      582374.919
     1889965.116      581888.878     1889943.671      581721.919
     1889822.686      581483.987     1889843.531      581341.577
     1889959.023      581314.661     1890079.727       581200.91
      1890315.93      580801.473     1890564.282      580719.854
     1890602.491      580650.387     1890638.972      580270.049
     1890732.432      580052.162     1890545.206      579656.988
     1890586.153      578955.388     1890680.891      578877.257
     1890840.534      578878.566     1890899.419      578680.321
     1891044.891       578633.28     1891123.607      578506.129
     1891132.248      578347.526     1891686.273       577783.11
     1891820.007      577486.212     1891802.651      577029.382
     1892102.573      576895.736      1892132.07      576346.528
     1892417.487      575402.103     1892304.445      575018.105
     1893372.518      574203.401     1893816.828      573992.585

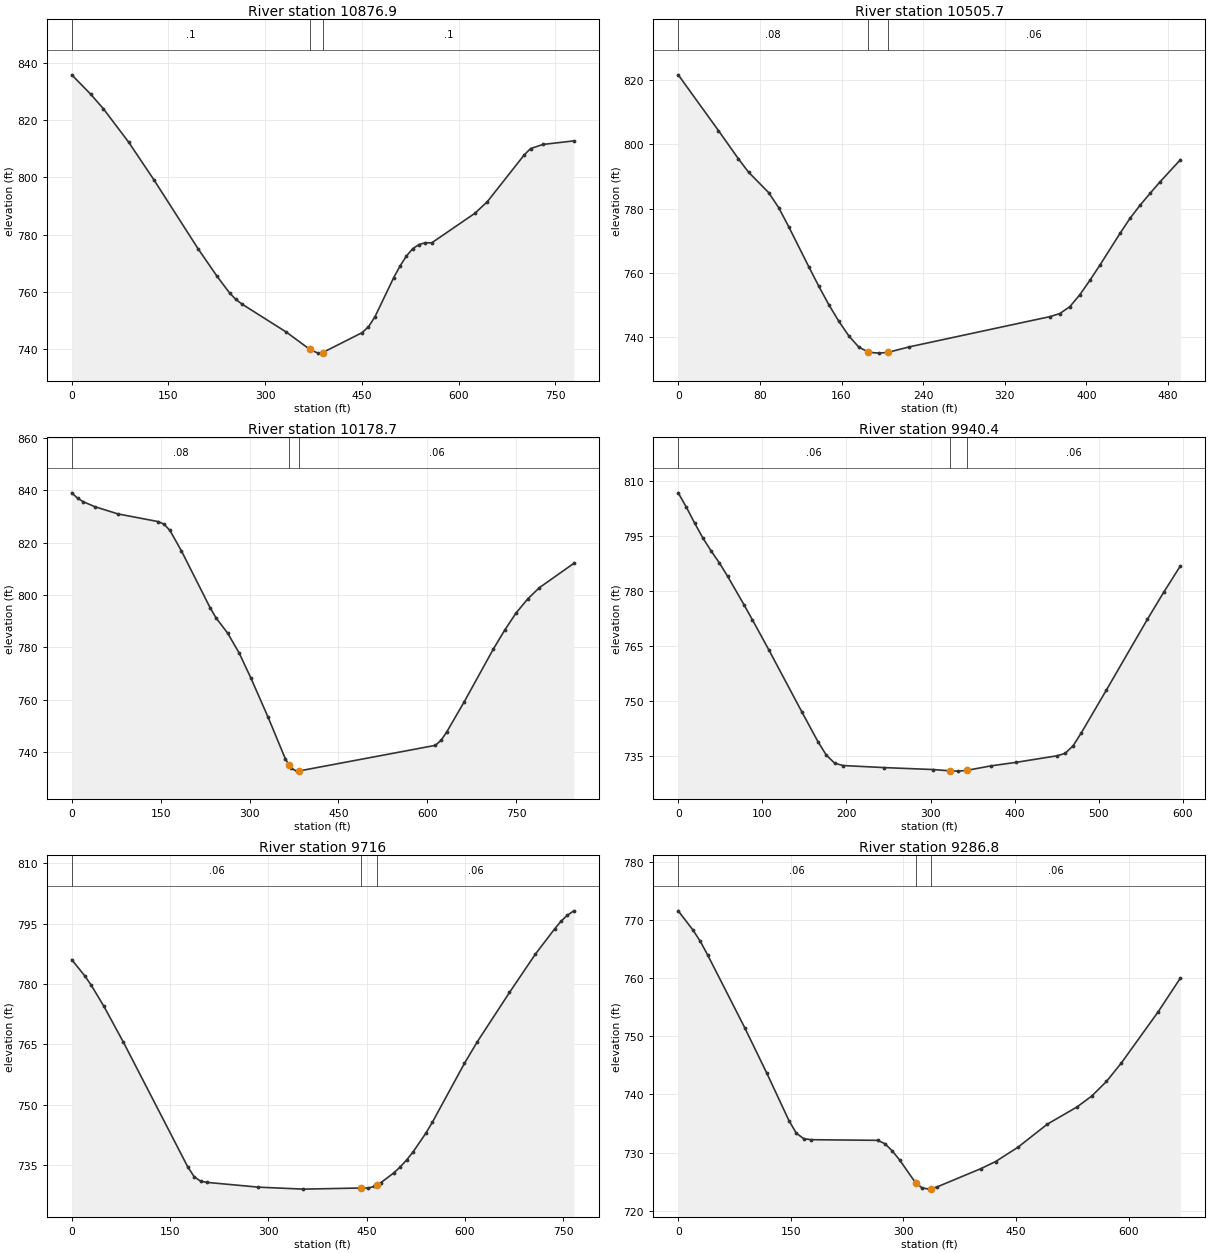
Type RM Length L Ch R = 1 ,10876.9 ,395.2,370.9,346.6
XS GIS Cut Line= 3
     1889968.546      582772.215     1889692.836      582286.965
     1889490.648      582198.738
#Sta/Elev= 30
       0  835.78    29.4     829      49  823.94    88.1  812.31   127.3  799.15
   195.8  775.08   225.2  765.47   244.8   759.6   254.6  757.32   264.4  755.66
   332.9  745.92   369.2  739.89   381.9  738.59   389.2  738.79   450.4  745.76
   460.2   747.8     470  751.19   499.4     765   509.2  769.03   518.9  772.46
   528.7  775.06   538.5  776.49   548.3  777.15   558.1  777.07   625.2  787.42
   644.4  791.45     702  807.89   711.6  810.02   730.8  811.47   778.7  812.71
#Mann= 3 , 0 , 0
       0      .1       0   369.2    .045       0   389.2      .1       0
Bank Sta=369.2,389.2
XS Rating Curve= 0 ,0
Exp/Cntr=0.3,0.1

Type RM Length L Ch R = 1 ,10505.7 ,332.1,326.9,321.7
XS GIS Cut Line= 2
     1890090.218      582130.945     1889600.143       582087.52
#Sta/Elev= 30
       0  821.63    39.4  804.31      59   795.5    68.9  791.36    88.6  785.02
    98.4  780.35   108.2  774.45   127.9  761.98   137.8  755.87   147.6  750.14
   157.4  744.99   167.3   740.4   177.1  736.92   185.5  735.59     187  735.35
   196.8   735.1   205.5  735.34   226.3  737.04   364.1  746.44   373.9   747.4
   383.8  749.57   393.6  753.28   403.4  757.74   413.3  762.51     433  772.38
   442.8  777.05   452.6   781.1   462.5  784.83   472.3  788.42     492   795.2
#Mann= 3 , 0 , 0
       0     .08       0   185.5    .045       0   205.5     .06       0
Bank Sta=185.5,205.5
XS Rating Curve= 0 ,0
Exp/Cntr=0.3,0.1

Type RM Length L Ch R = 1 ,10178.7 ,228.4,236.8,245
XS GIS Cut Line= 2
     1890328.018        581754.6     1889486.412      581853.856
#Sta/Elev= 30
       0  838.94     9.7   836.9    19.5  835.54      39  833.65    77.9   830.9
   146.1  827.96   155.8  826.96   165.6  824.62   185.1   816.8   233.8     795
   243.5  791.26     263  785.48   282.5  777.87     302  768.48   331.2  753.47
   360.4  737.57  366.43  735.25   370.2  733.93   379.9  732.83   383.9  732.91
   613.7  742.66   623.4  744.62   633.1  747.86   662.4  759.28   711.1  779.21
   730.6  786.56     750  793.16   769.5  798.47     789  802.74   847.4  812.06
#Mann= 3 , 0 , 0
       0     .08       0  366.43    .045       0   383.9     .06       0
Bank Sta=366.43,383.9
XS Rating Curve= 0 ,0
Exp/Cntr=0.3,0.1

Type RM Length L Ch R = 1 ,9940.4  ,224.6,225,225.6
XS GIS Cut Line= 2
     1890203.948      581626.395      1889612.55       581545.75
#Sta/Elev= 30
       0  806.75     9.8  802.77    19.6  798.45    29.4  794.37    39.1   790.9
    48.9  787.61    58.7  783.97    78.3  776.14    88.1  772.11   107.6  763.91
   146.8     747   166.3  738.72   176.1  735.11   185.9  732.95   195.7  732.28
   244.6  731.72   303.3  731.18   323.3  730.83   332.7  730.75   343.3  730.97
   371.8  732.19   401.2  733.13   450.1  734.93   459.9  735.59   469.7  737.74
   479.4  741.29   508.8  752.81   557.7  772.19   577.3  779.64   596.9  786.77
#Mann= 3 , 0 , 0
       0     .06       0   323.3    .045       0   343.3     .06       0
Bank Sta=323.3,343.3
XS Rating Curve= 0 ,0
Exp/Cntr=0.3,0.1

Type RM Length L Ch R = 1 ,9716    ,426.7,429.1,431.4
XS GIS Cut Line= 2
     1890275.058      581475.099     1889528.803       581302.32
#Sta/Elev= 30
       0  786.02    19.6  782.05    29.5  779.73    49.1  774.41    78.6  765.57
   176.8  734.58   186.6  732.12   196.4  730.99   206.2  730.68   284.8  729.49
   353.5     729   441.9  729.28   451.7  729.27   461.6  729.66   466.2   730.1
   471.4  730.59     491  732.99   500.8  734.47   510.7  736.22   520.5   738.2
   540.1  742.88     550  745.58     599  760.23   618.7  765.62   667.8  777.87
   707.1  787.35   736.5  793.63   746.4  795.57   756.2  797.08     766  798.16
#Mann= 3 , 0 , 0
       0     .06       0   441.9    .045       0   466.2     .06       0
Bank Sta=441.9,466.2
XS Rating Curve= 0 ,0
Exp/Cntr=0.3,0.1

Type RM Length L Ch R = 1 ,9286.8  ,339.1,348.8,358.4
XS GIS Cut Line= 2
     1890451.513      581206.741     1889811.865      581011.906
#Sta/Elev= 30
       0  771.56    19.7  768.24    29.5  766.29    39.3  763.94    88.5  751.48
     118  743.64   147.5  735.48   157.3  733.32   167.2  732.38     177  732.21
   265.5   732.1   275.3  731.52   285.2  730.26     295   728.7   314.7  725.06
     317  724.79   324.5  723.93   334.3  723.71     337  723.81   344.2  724.06
   403.2  727.24   422.8  728.46   452.3   730.9   491.7  734.89     531  737.83
   550.7  739.71   570.3  742.22     590  745.37   639.2   754.2   668.7  759.98
#Mann= 3 , 0 , 0
       0     .06       0     317    .045       0     337     .06       0
Bank Sta=317,337
XS Rating Curve= 0 ,0
Exp/Cntr=0.3,0.1

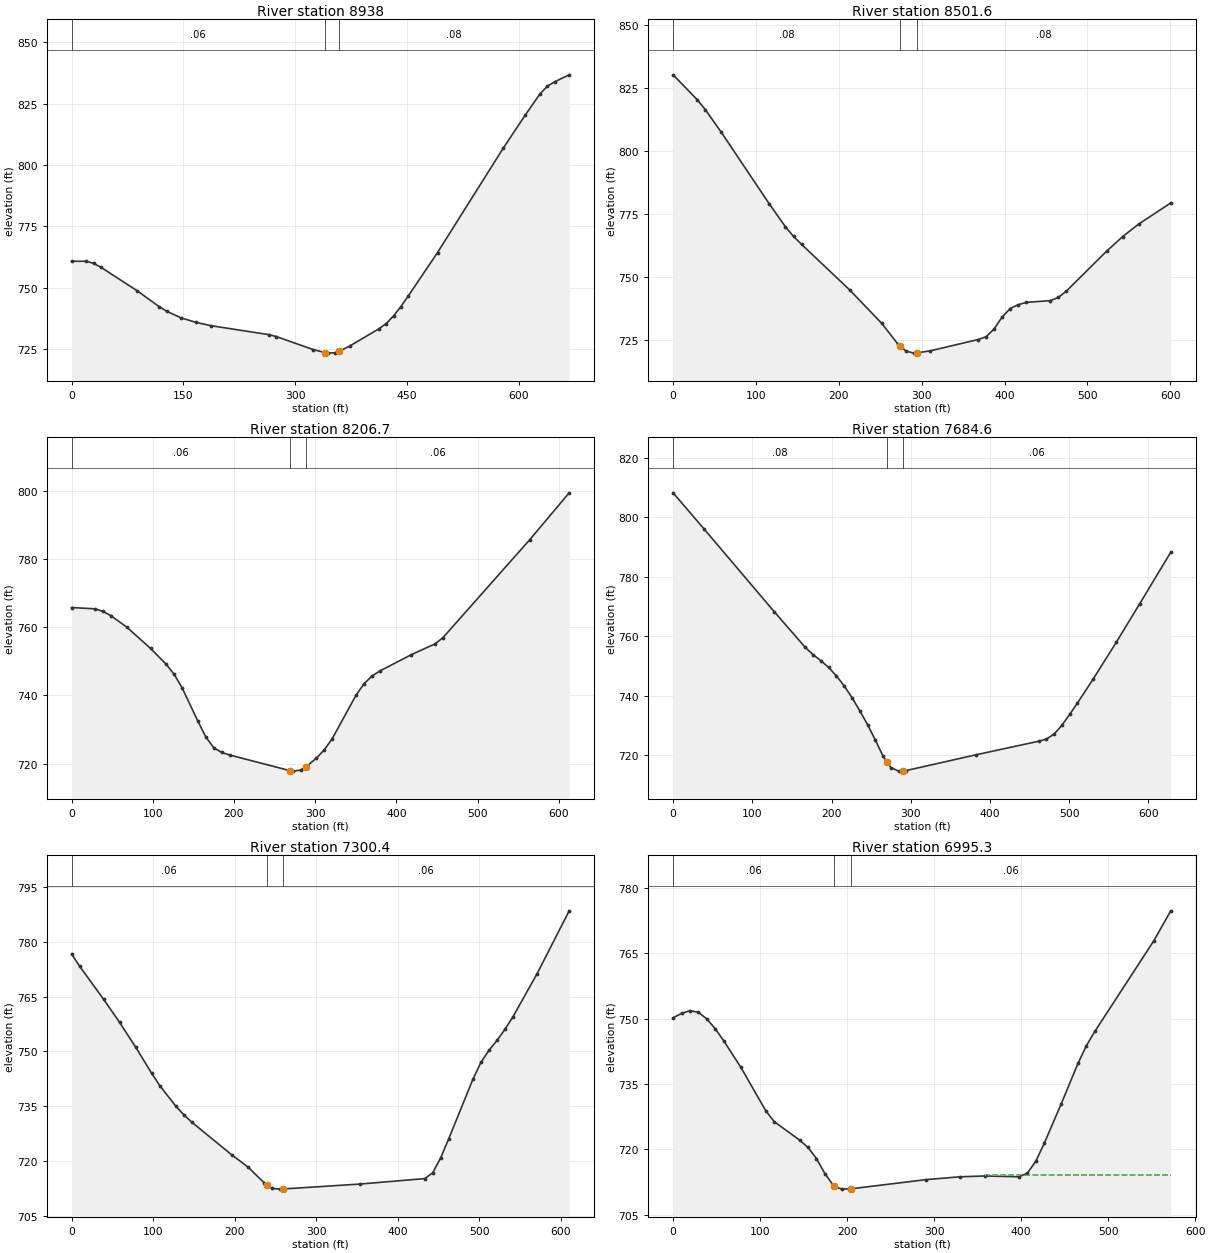
Type RM Length L Ch R = 1 ,8938    ,446.2,436.3,426.4
XS GIS Cut Line= 2
     1890582.361      581028.793     1890061.268      580611.092
#Sta/Elev= 30
       0  760.79    19.6   760.8    29.5  759.95    39.3  758.37    88.4   748.7
   117.8  742.26   127.7  740.42   147.3   737.7     167  735.89   186.6  734.57
   265.2  730.87     275  730.09   324.1  724.83   339.5  723.61   343.7  723.36
   353.6  723.55   359.5  724.16   373.2  726.23   412.5  733.28   422.3  735.43
   432.1  738.51     442  742.35   451.8  746.62   491.1  764.33   579.4  806.92
   608.9  820.39   628.6  828.98   638.4   832.1   648.2  833.91   667.8  836.77
#Mann= 3 , 0 , 0
       0     .06       0   339.5    .045       0   359.5     .08       0
Bank Sta=339.5,359.5
XS Rating Curve= 0 ,0
Exp/Cntr=0.3,0.1

Type RM Length L Ch R = 1 ,8501.6  ,305.6,294.8,284
XS GIS Cut Line= 2
     1890876.796      580659.916     1890301.136       580489.09
#Sta/Elev= 30
       0  830.18    29.1  820.31    38.7  816.42    58.1  807.41   116.2  778.89
   135.6  769.85   145.3  766.07     155  762.91   213.1  744.81   251.8  731.55
   271.2  723.36   273.7  722.64   280.9  720.58   290.6  719.75   293.7  719.83
   309.9  720.63     368  725.14   377.7  726.26   387.4  729.38   397.1  734.11
   406.8  737.45   416.5  738.97   426.1  739.89   455.2  740.58   464.9  741.85
   474.6  744.38     523  760.16   542.4  765.99   561.7  770.92   600.5  779.35
#Mann= 3 , 0 , 0
       0     .08       0   273.7    .045       0   293.7     .08       0
Bank Sta=273.7,293.7
XS Rating Curve= 0 ,0
Exp/Cntr=0.3,0.1

Type RM Length L Ch R = 1 ,8206.7  ,529.4,521.8,514.2
XS GIS Cut Line= 2
     1890915.281      580255.426     1890308.144      580339.173
#Sta/Elev= 30
       0   765.8    29.2  765.41    38.9  764.65    48.6  763.38    68.1  760.04
    97.3   753.8   116.7  749.12   126.5  746.16   136.2  742.23   155.6  732.46
   165.4  727.82   175.1  724.68   184.8  723.29   194.6  722.54   268.9  717.94
   272.4   717.8   282.1   718.1   288.9  719.07   301.6  721.61   311.3  724.07
     321  727.28   350.2     740     360  743.36   369.7  745.65   379.4  747.14
   418.3  751.95   447.5  755.12   457.2   756.9   564.2  785.66   612.9  799.45
#Mann= 3 , 0 , 0
       0     .06       0   268.9    .045       0   288.9     .06       0
Bank Sta=268.9,288.9
XS Rating Curve= 0 ,0
Exp/Cntr=0.3,0.1

Type RM Length L Ch R = 1 ,7684.6  ,372.3,384.2,396
XS GIS Cut Line= 2
     1890865.538      579706.188     1890299.413      579978.222
#Sta/Elev= 30
       0  808.21    39.3  795.99   127.6  768.29   166.8  756.29   176.6  753.86
   186.5  751.83   196.3  749.55   206.1   746.7   215.9  743.38   225.7  739.42
   235.5  735.05   245.4  730.34   255.2   725.2     265  719.71   269.6  717.94
   274.8  715.93   284.6  714.72   289.6  714.83   294.4  714.93   382.7  720.23
   461.3  724.76   471.1  725.48   480.9  727.18   490.7  730.12   500.5  733.76
   510.3  737.59     530  745.57   559.4  758.02   588.8  770.89   628.1  788.27
#Mann= 3 , 0 , 0
       0     .08       0   269.6    .045       0   289.6     .06       0
Bank Sta=269.6,289.6
XS Rating Curve= 0 ,0
Exp/Cntr=0.3,0.1

Type RM Length L Ch R = 1 ,7300.4  ,303.8,305.1,306.4
XS GIS Cut Line= 2
     1890791.211      579463.448     1890181.202      579448.973
#Sta/Elev= 30
       0  776.67     9.8  773.32    39.4  764.21      59  757.89    78.7  751.11
    98.4  743.94   108.3  740.56   127.9  734.98   137.8   732.6   147.6  730.57
   196.8   721.6   216.5   718.3   236.2     714   239.4   713.5     246  712.48
   255.9  712.28   259.4  712.32   354.3  713.68     433  715.16   442.9  716.76
   452.7  720.87   462.6  726.11   492.1  742.32   501.9  746.94   511.8  750.26
   521.6  752.96   531.4  755.99   541.3  759.47   570.8  771.23   610.2  788.45
#Mann= 3 , 0 , 0
       0     .06       0   239.4    .045       0   259.4     .06       0
Bank Sta=239.4,259.4
XS Rating Curve= 0 ,0
Exp/Cntr=0.3,0.1

Type RM Length L Ch R = 1 ,6995.3  ,426.1,440.4,427
XS GIS Cut Line= 2
      1890797.07      579177.513     1890226.694      579134.663
#Sta/Elev= 30
       0  750.19     9.7  751.18    19.4  751.83    29.1  751.42    38.8  749.91
    48.5  747.64    58.2  744.89    77.6  738.89   106.6  728.81   116.3  726.32
   145.4   722.1   155.1   720.4   164.8  717.85   174.5  714.39     185  711.48
   193.9  710.84     205  710.93   290.8  713.02   329.6  713.67   358.7  713.86
   397.5  713.68   407.2   714.5   416.9  717.25   426.6  721.36     446  730.36
   465.3  739.69     475  743.75   484.7  747.04   552.6  767.88     572  774.74
#Mann= 3 , 0 , 0
       0     .06       0     185    .045       0     205     .06       0
#XS Ineff= 2 , 0
                          358.59          714.18
Permanent Ineff=
       F       F
Bank Sta=185,205
XS Rating Curve= 0 ,0
Exp/Cntr=0.3,0.1

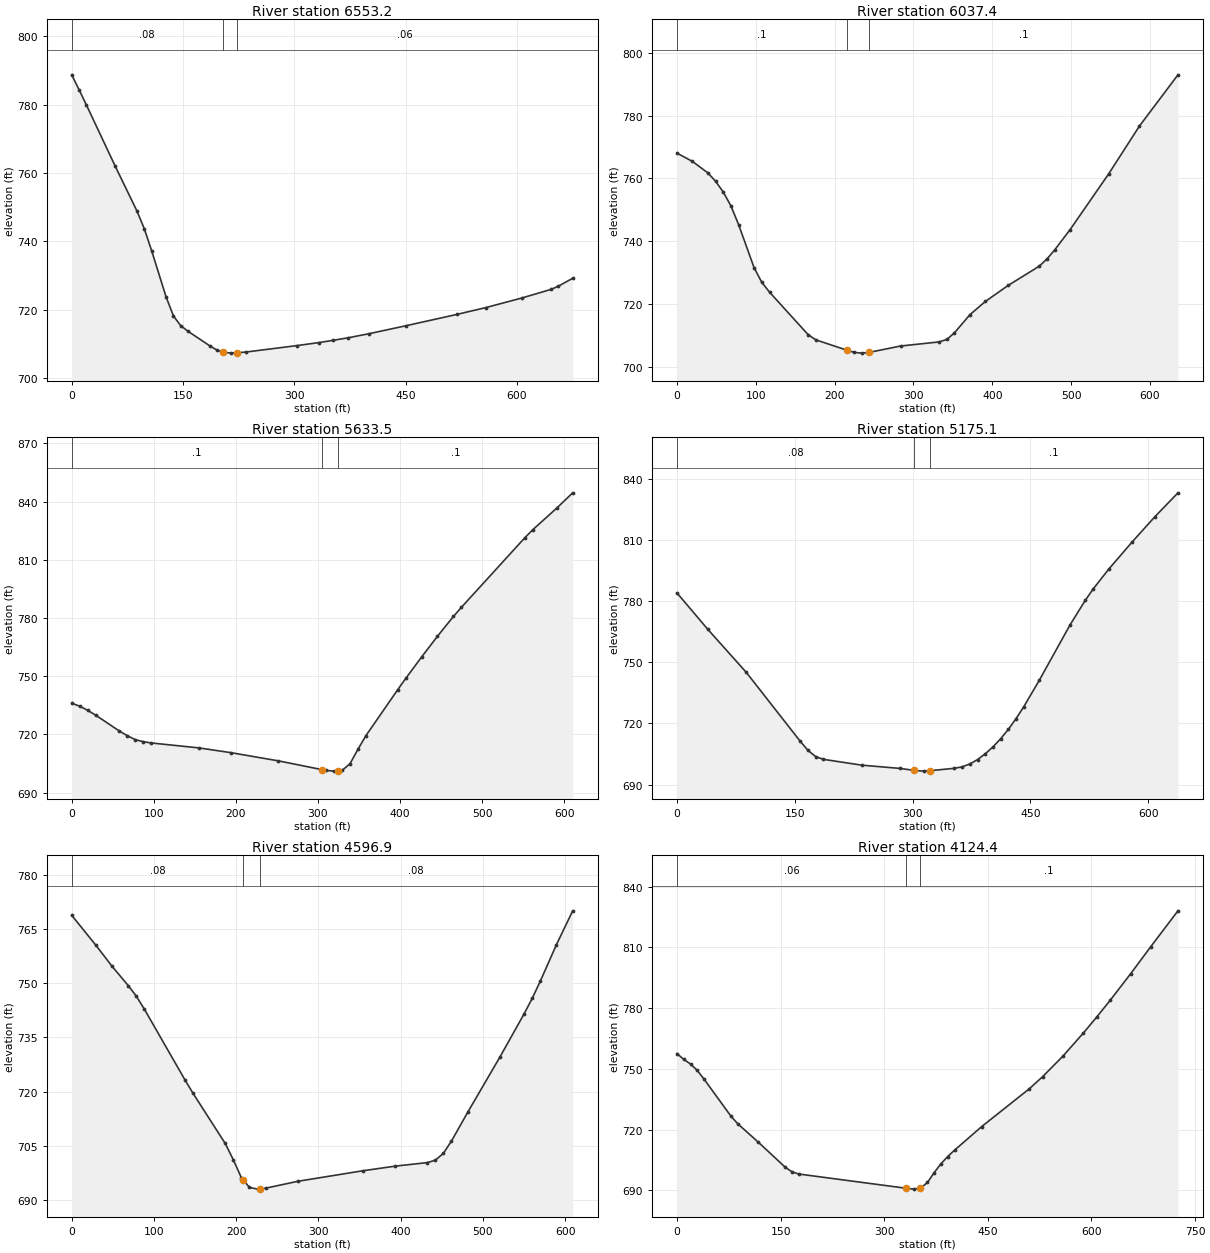
Type RM Length L Ch R = 1 ,6553.2  ,513.6,515.8,545.4
XS GIS Cut Line= 2
     1890950.434      579020.933     1890411.076      578615.064
#Sta/Elev= 30
       0  788.72     9.8  784.41    19.6  779.99    58.7  761.93      88  748.81
    97.8  743.66   107.6  737.28   127.2  723.68     137  718.16   146.7  715.32
   156.5  713.67   185.9  709.41   195.6  708.15   203.2  707.61   205.4  707.46
   215.2  707.25   223.2  707.36   234.8  707.57   303.3  709.45   332.6  710.32
   352.2     711   371.7  711.71   401.1  712.96     450  715.25   518.5  718.56
   557.6  720.56   606.5  723.39   645.7   725.9   655.4  726.81     675  729.16
#Mann= 3 , 0 , 0
       0     .08       0   203.2    .045       0   223.2     .06       0
Bank Sta=203.2,223.2
XS Rating Curve= 0 ,0
Exp/Cntr=0.3,0.1

Type RM Length L Ch R = 1 ,6037.4  ,404.7,402.7,400.7
XS GIS Cut Line= 2
     1891256.587      578721.672     1890778.689      578302.593
#Sta/Elev= 30
       0  768.04    19.6  765.39    39.1  761.76    48.9   759.1    58.7  755.65
    68.4  751.26    78.2  745.26    97.8  731.58   107.6   726.9   117.4  723.78
   166.2  710.29     176   708.6   215.1  705.34   224.9  704.59   234.7  704.36
   243.3  704.57   283.6  706.62   332.5  707.93   342.3   708.7     352  710.82
   371.6  716.58   391.2   720.8   420.5  725.97   459.6  732.03   469.4  734.34
   479.2  737.22   498.7  743.66   547.6  761.39   586.7  776.64   635.6  792.96
#Mann= 3 , 0 , 0
       0      .1       0   215.1    .045       0   243.3      .1       0
Bank Sta=215.1,243.3
XS Rating Curve= 0 ,0
Exp/Cntr=0.3,0.1

Type RM Length L Ch R = 1 ,5633.5  ,467.7,458.2,448.9
XS GIS Cut Line= 2
     1891482.669       578419.08     1891001.096      578044.114
#Sta/Elev= 30
       0   736.1     9.7  734.58    19.4  732.44    29.1  729.98    58.1  721.75
    67.8  719.36    77.5  717.34    87.2  716.27    96.9  715.63     155  713.08
   193.8  710.64   251.9   706.4   304.8   701.9     310  701.47   319.7  701.12
   324.8   701.3   329.4  701.47   339.1     705   348.8  712.44   358.4  719.38
   397.2   743.1   406.9  748.87   426.3  759.96   445.6  770.61     465  780.79
   474.7  785.49   552.2  821.44   561.9  825.56     591  836.66   610.3  844.48
#Mann= 3 , 0 , 0
       0      .1       0   304.8    .045       0   324.8      .1       0
Bank Sta=304.8,324.8
XS Rating Curve= 0 ,0
Exp/Cntr=0.3,0.1

Type RM Length L Ch R = 1 ,5175.1  ,586.7,578.1,569.3
XS GIS Cut Line= 2
     1891841.667      577982.884     1891231.658      577796.779
#Sta/Elev= 30
       0  784.03    39.2  766.21    88.3  745.04     157  711.23   166.8  706.79
   176.6  703.74   186.4  702.41   235.5  699.55   284.5  697.94   301.8     697
     314  696.63   321.8  696.84   353.2  698.01     363  698.73   372.8  700.13
   382.7   702.3   392.5  705.14   402.3  708.52   412.1  712.53   421.9  717.14
   431.7  722.39   441.5  728.22   461.2  741.15   500.4  768.34     520  780.52
   529.8  785.94   549.5  795.63   578.9  808.79   608.3  821.37   637.8  833.14
#Mann= 3 , 0 , 0
       0     .08       0   301.8    .045       0   321.8      .1       0
Bank Sta=301.8,321.8
XS Rating Curve= 0 ,0
Exp/Cntr=0.3,0.1

Type RM Length L Ch R = 1 ,4596.9  ,451,472.7,494.3
XS GIS Cut Line= 2
     1892036.043      577403.892     1891428.102      577441.113
#Sta/Elev= 30
       0  768.86    29.5  760.53    49.1  754.71    68.8  749.36    78.6  746.42
    88.4  742.82   137.5  723.31   147.4  719.55   186.6  705.63   196.5  701.09
   206.3  696.11   208.4  695.54   216.1  693.43     226  692.96   228.4  693.02
   235.8  693.22   275.1  695.14   353.7  698.04     393  699.32   432.2  700.31
   442.1  700.97   451.9  702.89   461.7  706.28   481.4  714.24   520.7  729.61
   550.1  741.58     560  745.89   569.8  750.65   589.4  760.76   609.1   770.1
#Mann= 3 , 0 , 0
       0     .08       0   208.4    .045       0   228.4     .08       0
Bank Sta=208.4,228.4
XS Rating Curve= 0 ,0
Exp/Cntr=0.3,0.1

Type RM Length L Ch R = 1 ,4124.4  ,559.4,538.1,516.8
XS GIS Cut Line= 2
     1892106.923      577223.187      1891595.94      576708.528
#Sta/Elev= 30
       0  757.56     9.8  754.72    19.6  752.42    29.4  749.23    39.2  744.95
    78.4  726.54    88.2  722.84   117.6  713.86   156.8  701.44   166.6  699.17
   176.4   698.1   331.5  691.09     343  690.65   351.5  691.13   352.8   691.2
   362.6  693.95   372.4  698.83   382.2  703.21     392  706.75   401.8  709.88
     441   721.5   509.6  740.07   529.2  746.13   558.6  756.28     588   767.6
   607.6  775.61   627.2  783.92   656.6  796.93     686  810.42   725.2  828.04
#Mann= 3 , 0 , 0
       0     .06       0   331.5    .045       0   351.5      .1       0
Bank Sta=331.5,351.5
XS Rating Curve= 0 ,0
Exp/Cntr=0.3,0.1

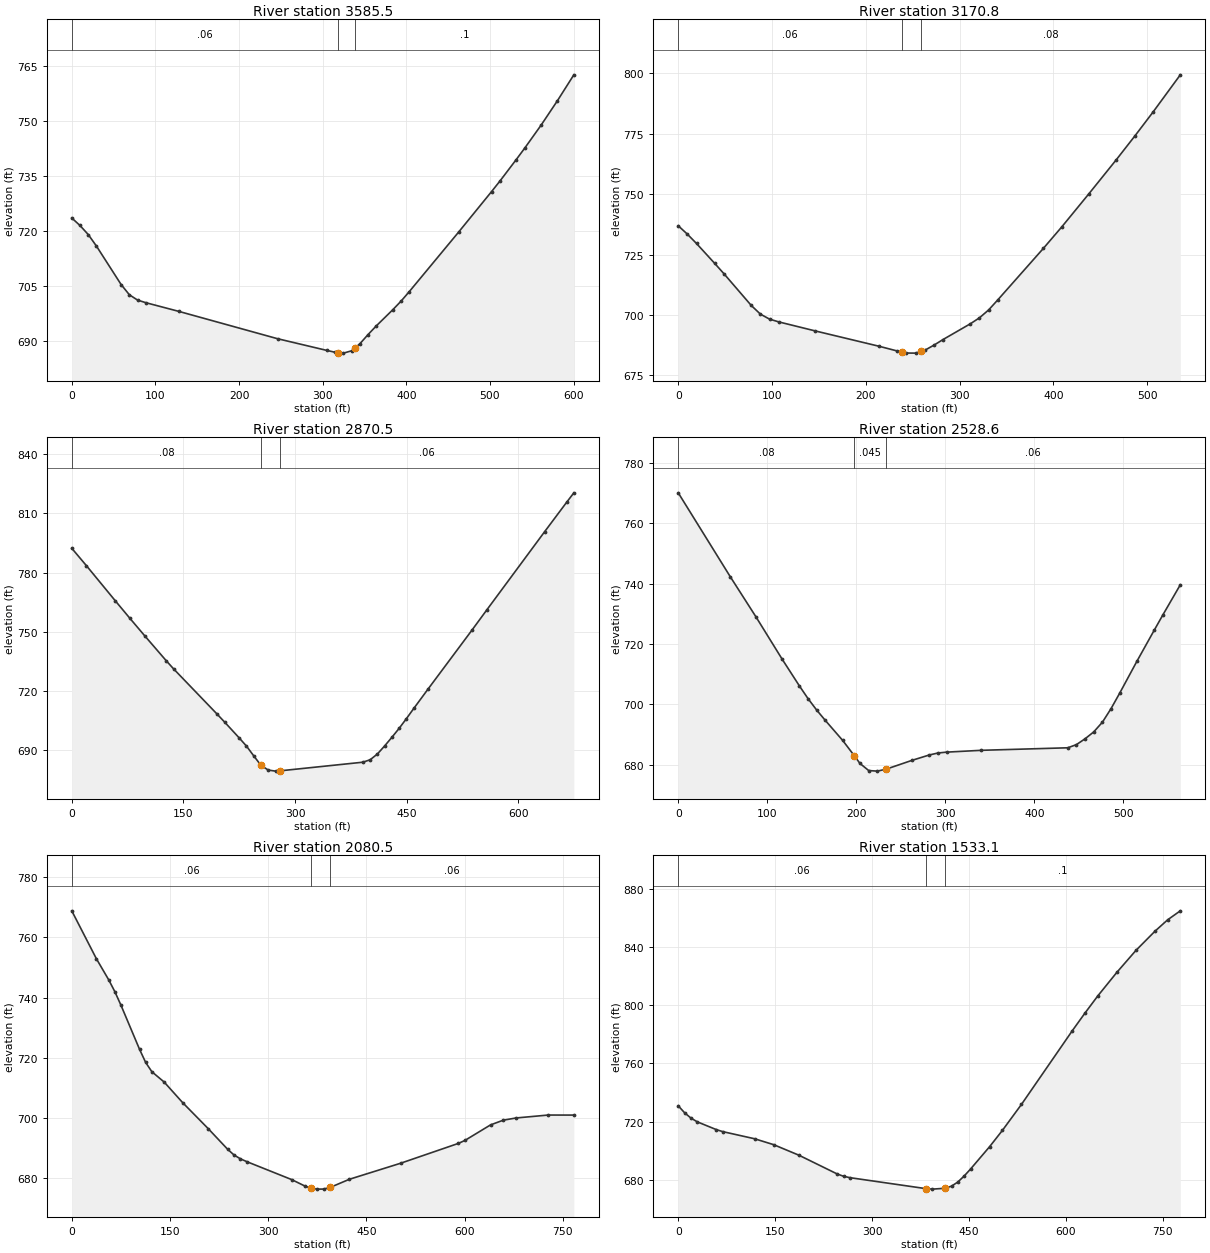
Type RM Length L Ch R = 1 ,3585.5  ,405.4,414.6,423.9
XS GIS Cut Line= 2
     1892419.395      576623.517     1891820.185      576660.278
#Sta/Elev= 30
       0  723.56     9.8  721.51    19.7  719.04    29.5   715.9      59  705.42
    68.9  702.62    78.7  701.18    88.6  700.47   127.9  698.11     246  690.66
   305.1  687.46   314.9  686.96   318.4  686.88   324.8  686.73   334.6  687.36
   338.4   688.1   344.5  689.29   354.3   691.8   364.1  694.15   383.8  698.55
   393.7  700.89   403.5  703.48   462.6  719.73   501.9  730.74   511.8  733.58
   531.4  739.46   541.3   742.5     561   748.8   580.6  755.48   600.3  762.56
#Mann= 3 , 0 , 0
       0     .06       0   318.4    .045       0   338.4      .1       0
Bank Sta=318.4,338.4
XS Rating Curve= 0 ,0
Exp/Cntr=0.3,0.1

Type RM Length L Ch R = 1 ,3170.8  ,309.4,300,290.6
XS GIS Cut Line= 2
      1892414.57      576335.859     1891903.702      576175.603
#Sta/Elev= 30
       0  736.96     9.7   733.5    19.5  729.62    38.9  721.38    48.7  717.13
    77.9  703.96    87.6  700.39    97.4  698.31   107.1  697.18     146  693.44
   214.2  687.08   233.6  685.12   238.8  684.67   243.4  684.28   253.1  684.24
   258.8  684.92   262.8   685.4   272.6  687.52   282.3  689.85   311.5  696.39
   321.2  698.85     331  702.12   340.7  706.25   389.4  727.61   408.9  736.45
   438.1  750.29   467.3  764.37   486.7  774.01   506.2  783.97   535.4  799.44
#Mann= 3 , 0 , 0
       0     .06       0   238.8    .045       0   258.8     .08       0
Bank Sta=238.8,258.8
XS Rating Curve= 0 ,0
Exp/Cntr=0.3,0.1

Type RM Length L Ch R = 1 ,2870.5  ,332.9,341.9,351
XS GIS Cut Line= 2
     1892532.207      575960.893     1891859.474      576008.683
#Sta/Elev= 30
       0  792.31    19.6  783.51    58.6  765.58    78.2  756.69    97.7     748
   127.1  735.12   136.8  731.07   195.5     708   205.3  704.07   224.8  696.06
   234.6   691.9   244.4  686.93   254.1  682.12   263.9   679.7   273.7  679.16
     280  679.32     391  683.69   400.8  684.93   410.5  687.85   420.3  691.97
   430.1  696.38   439.8  700.91   449.6  705.86   459.4  710.99   478.9     721
   537.6  750.77   557.1  760.82   635.3   800.8   664.6   815.6   674.4  820.46
#Mann= 3 , 0 , 0
       0     .08       0   254.1    .045       0     280     .06       0
Bank Sta=254.1,280
XS Rating Curve= 0 ,0
Exp/Cntr=0.3,0.1

Type RM Length L Ch R = 1 ,2528.6  ,453.3,448,442.5
XS GIS Cut Line= 2
     1892539.559      575714.592     1891999.167      575552.842
#Sta/Elev= 30
       0  770.13    58.4  742.34    87.5  728.92   116.7  714.99   136.2  706.07
   145.9  701.86   155.6  698.07   165.3  694.64   184.8  688.01     198  682.88
   204.2  680.38     214  678.03   223.7  677.84   233.4  678.47   262.6  681.41
     282  683.19   291.8  683.85   301.5  684.14   340.4  684.74   437.6  685.58
   447.4  686.63   457.1  688.57   466.8  690.84   476.6  694.08   486.3  698.58
     496   703.7   515.4  714.31   534.9  724.63   544.6   729.7   564.1  739.64
#Mann= 3 , 0 , 0
       0     .08       0     198    .045       0   233.4     .06       0
Bank Sta=198,233.4
XS Rating Curve= 0 ,0
Exp/Cntr=0.3,0.1

Type RM Length L Ch R = 1 ,2080.5  ,522.3,546.8,571.7
XS GIS Cut Line= 3
     1892734.394      575306.541     1892581.949      575232.674
     1891984.462      575225.666
#Sta/Elev= 30
       0  768.85    37.6  752.93    56.5  745.89    65.9  741.94    75.3   737.4
   103.5  722.84   112.9  718.45   122.3  715.39   141.2  711.93   169.4   705.1
   208.6  696.42     238  689.63   247.8  687.71   257.6  686.43   267.4  685.49
   335.9  679.53   355.5  677.45   365.3  676.65   375.1  676.36   384.9  676.38
   394.7  676.93   424.1  679.64   502.4  684.97   590.6  691.56   600.4  692.53
   639.6   697.7   659.2  699.28   678.8  700.01   727.7  700.98   766.9  700.97
#Mann= 3 , 0 , 0
       0     .06       0   365.3    .045       0   394.7     .06       0
Bank Sta=365.3,394.7
XS Rating Curve= 0 ,0
Exp/Cntr=0.3,0.1

Type RM Length L Ch R = 1 ,1533.1  ,526.3,525.1,523.9
XS GIS Cut Line= 2
     1892745.652      575156.049     1892355.982      574483.316
#Sta/Elev= 30
       0  730.84     9.8  726.08    19.7  722.39    29.5  719.81      59  714.47
    68.9  713.09   118.1   708.2   147.6  704.15     187  696.85     246  684.01
   255.9   682.4   265.7  681.45   383.8  673.88   393.6  673.56   413.3  674.15
   423.2  675.61     433  678.48   442.8  682.61   452.7  687.41   482.2  702.78
   501.9  713.92   531.4  731.77   610.1  782.41   629.8   794.6   649.5  806.31
     679   822.5   708.6  837.62   738.1  850.83   757.8   858.7   777.4  864.87
#Mann= 3 , 0 , 0
       0     .06       0   383.8    .045       0   413.3      .1       0
Bank Sta=383.8,413.3
XS Rating Curve= 0 ,0
Exp/Cntr=0.3,0.1

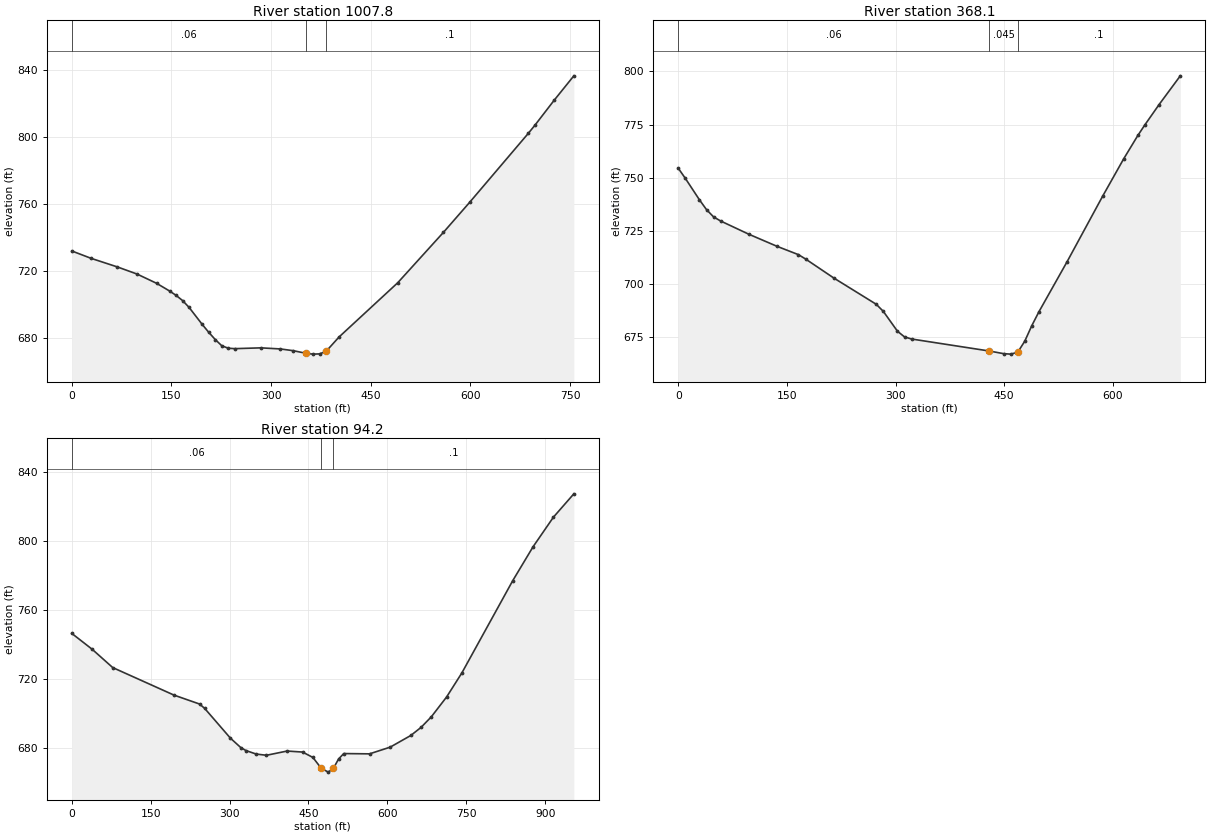
Type RM Length L Ch R = 1 ,1007.8  ,635.4,639.5,643.7
XS GIS Cut Line= 2
     1893174.331      574818.815      1892746.98      574195.709
#Sta/Elev= 30
       0  732.03    29.4  727.59    68.7   722.5    98.1  718.29   127.6  712.76
   147.2  708.16     157  705.55   166.8  702.45   176.6  698.36   196.2   688.3
   206.1  683.55   215.9  679.23   225.7  675.55   235.5  674.05   245.3  673.79
   284.6  674.27     314  673.62   333.6  672.56   353.2  670.97   363.1  670.53
   372.9  670.67   382.7  672.17   402.3  680.77   490.6  713.09   559.3   743.1
   598.6  760.93   686.9  802.06   696.7  806.82   726.1  821.93   755.6  836.43
#Mann= 3 , 0 , 0
       0     .06       0   353.2    .045       0   382.7      .1       0
Bank Sta=353.2,382.7
XS Rating Curve= 0 ,0
Exp/Cntr=0.3,0.1

Type RM Length L Ch R = 1 ,368.1   ,276,273.8,271.5
XS GIS Cut Line= 2
     1893675.434      574557.579     1893383.181       573928.96
#Sta/Elev= 30
       0  754.42     9.8  749.64    29.3  739.52    39.1  734.88    48.8  731.48
    58.6  729.54    97.6   723.3   136.7  717.58     166  713.69   175.8  711.65
   214.8  702.69   273.4  690.32   283.2  686.96   302.7  677.62   312.4  674.96
   322.2  673.96   429.6   668.3   449.1  667.07   458.9  666.84   468.7  667.72
   478.4  672.91   488.2  680.28     498   686.8     537  710.45   585.8  741.13
   615.1  758.88   634.6  769.86   644.4  774.89   663.9   784.4   693.2  797.93
#Mann= 3 , 0 , 0
       0     .06       0   429.6    .045       0   468.7      .1       0
Bank Sta=429.6,468.7
XS Rating Curve= 0 ,0
Exp/Cntr=0.3,0.1

Type RM Length L Ch R = 1 ,94.2    ,94.2,94.2,94.2
XS GIS Cut Line= 4
     1893806.397      574492.098     1893847.753       574232.93
      1893640.97      573877.264      1893365.26      573824.879
#Sta/Elev= 30
       0  746.58    38.9  737.33    77.8  726.74   194.4  710.74     243  705.56
   252.7  703.02   301.6  685.75   321.2  680.32     331  678.57   350.6  676.52
   370.2  675.82   409.4  678.27   438.8  677.68   458.4  674.55   474.3  668.25
   487.7  666.03   497.5  668.29   507.3  673.69   517.1  676.81   566.1  676.64
   605.3  680.53   644.5   687.3   664.1  692.03   683.5  698.13   712.6  709.66
   741.6  723.62   838.4  777.23   877.1  796.94   915.8   814.1   954.5  827.61
#Mann= 3 , 0 , 0
       0     .06       0   474.3    .045       0   497.5      .1       0
Bank Sta=474.3,497.5
XS Rating Curve= 0 ,0
Exp/Cntr=0.3,0.1

Chan Stop Cuts=-1
Use User Specified Reach Order=0
Composite Channel Slope=5